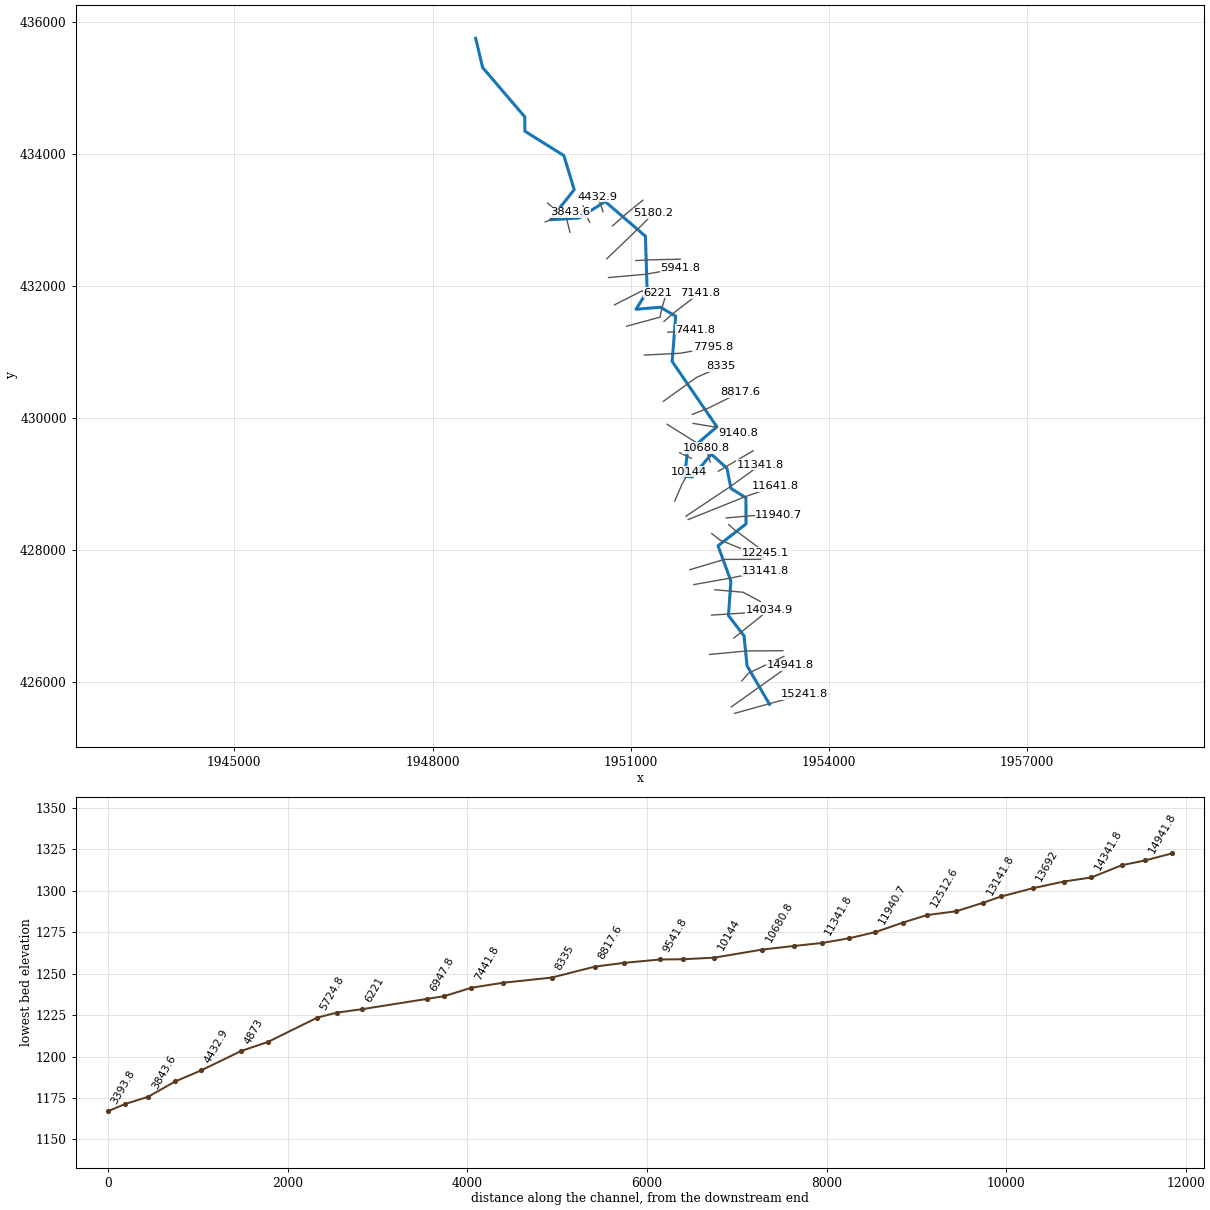
--- HrseshoeCk.prj (project) ---

Proj Title=HrseshoeCk
Current Plan=p01
Geom File=g01
Flow File=f01
Plan File=p01
DSS Export Rating Curves=0
DSS Export Rating Curve Sorted=0
DSS Export Volume Flow Curves=0
DXF OffsetX=0
DXF OffsetY=0
DXF ScaleX=0
DXF ScaleY=0

--- HrseshoeCk.p01 (plan) ---

Plan Title=Floodplain
Program Version=4.00
Geom File=g01
Flow File=f01
K Sum by GR=0
Std Step Tol=0.01
Critical Tol=0.01
Num of Std Step Trials=20
Max Error Tol=0.3
Flow Tol Ratio=0.001
Split Flow NTrial=30
Split Flow Tol=0.02
Split Flow Ratio=0.02
Log Output Level=0
Friction Slope Method=1
Unsteady Friction Slope Method=2
Unsteady Bridges Friction Slope Method=1
Global Log Level=0
CheckData=False
Run HTab=0
Run UNet=0
Run PostProcess=0
UNET Theta=0
UNET Theta Warmup=0
UNET ZTol=0
UNET ZSATol=0
UNET MxIter=0
UNET MaxInSteps=0
UNET DtIC=0
UNET DtMin=0
UNET MaxCRTS=0
UNET WFStab=0
UNET SFStab=0
UNET WFX=0
UNET SFX=0
UNET DSS MLevel=0
UNET DZMax Abort=0
UNET Convert EG Bridges=0
UNET Use Existing IB Tables=0
UNET Froude Limit=0
UNET Froude Power=0
Write IC File=0
Echo Input=False
Echo Output=False
Write Detailed=0

--- HrseshoeCk.f01 (steady flow) ---

Flow Title=NFF Regression Equation
Program Version=4.00
Number of Profiles=1
Profile Names=P100yr
River Rch & RM=HrseshoeCk,Main      ,15241.8
524.8080
River Rch & RM=HrseshoeCk,Main      ,14682.9
532.0906
River Rch & RM=HrseshoeCk,Main      ,13141.8
584.9089
River Rch & RM=HrseshoeCk,Main      ,12512.6
648.9396
River Rch & RM=HrseshoeCk,Main      ,9797.1
707.3737
River Rch & RM=HrseshoeCk,Main      ,5180.2
785.0205
River Rch & RM=HrseshoeCk,Main      ,4873
887.3473
River Rch & RM=HrseshoeCk,Main      ,291.1
976.1896
Boundary for River Rch & Prof#=HrseshoeCk,Main      ,1
Up Type=0
Dn Type=3
Dn Slope=0.187459

--- HrseshoeCk.g01 (geometry) ---

Geom Title=USGS 3m DEM
Program Version=4.00

River Reach=HrseshoeCk     ,Main
Reach XY= 30
     1953100.852      425654.942     1952759.870      426239.512
     1952715.347      426692.401     1952479.324      427000.429
     1952515.783      427524.734     1952321.338      428058.435
     1952744.781      428390.406     1952743.213      428786.887
     1952516.743      428928.540     1952456.755      429234.804
     1952219.817      429447.662     1951930.713      429102.859
     1951816.130      429115.012     1951857.176      429478.190
     1952303.977      429863.276     1951626.894      430854.595
     1951680.713      431540.359     1951448.074      431677.512
     1951080.019      431646.014     1951248.422      431915.359
     1951222.380      432753.901     1950613.005      433279.943
     1950218.908      433029.942     1949783.899      433003.599
     1950144.255      433460.498     1949988.133      433976.601
     1949398.568      434346.151     1949395.991      434564.665
     1948758.838      435311.192     1948653.323      435754.846

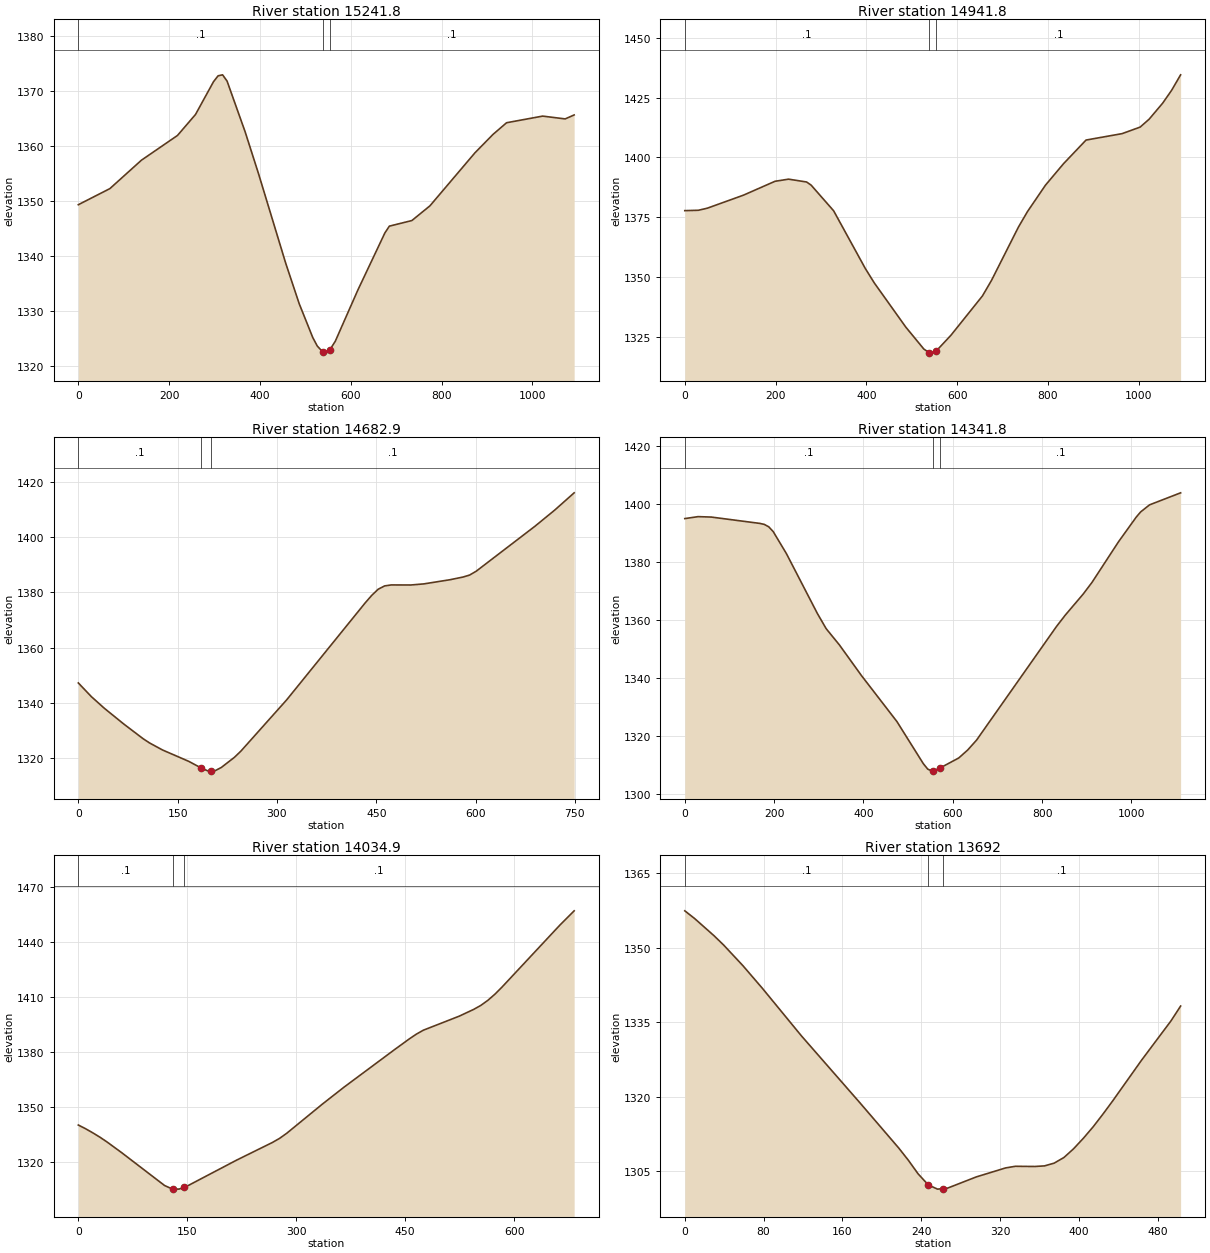
Type RM Length L Ch R = 1 ,15241.8,292.2,300,307.9
XS GIS Cut Line= 3
     1952572.410      425517.384     1953098.200      425664.584
     1953624.656      425809.358
#Sta/Elev= 30
       0 1349.37    69.5 1352.30   139.0 1357.47   218.4 1361.97   258.1 1365.79
   297.8 1371.76   307.8 1372.82   317.7 1373.00   327.6 1371.86   367.3 1362.65
   397.1 1354.95   456.7 1338.74   486.4 1331.37   516.2 1325.23   526.2 1323.67
   538.5 1322.56   546.0 1322.37   553.5 1322.91   565.9 1324.53   615.5 1333.82
   675.1 1344.23   685.0 1345.47   734.6 1346.49   774.3 1349.16   873.6 1358.82
   913.3 1362.16   943.1 1364.28  1022.5 1365.49  1072.2 1364.98  1092.0 1365.70
#Mann= 3 , 0 , 0
       0     0.1       0   538.5   0.045       0   553.5     0.1       0
Bank Sta=   538.5,   553.5
Exp/Cntr=0.3,0.1

Type RM Length L Ch R = 1 ,14941.8,262.9,258.9,255
XS GIS Cut Line= 3
     1952521.203      425615.231     1952966.439      425931.946
     1953410.623      426248.876
#Sta/Elev= 30
       0 1377.70    29.8 1377.85    49.7 1378.73   129.2 1384.17   198.7 1389.97
   228.5 1390.86   268.2 1389.68   278.2 1388.37   327.8 1377.64   397.4 1353.57
   417.2 1347.52   486.8 1328.99   526.5 1319.83   538.9 1318.24   546.4 1318.13
   553.9 1319.05   586.1 1325.59   655.5 1342.03   675.4 1348.51   734.9 1370.87
   754.7 1377.30   794.4 1388.36   834.1 1397.32   883.7 1407.21   963.1 1409.89
  1002.8 1412.62  1022.6 1415.92  1052.4 1422.62  1072.2 1428.02  1092.0 1434.48
#Mann= 3 , 0 , 0
       0     0.1       0   538.9   0.045       0   553.9     0.1       0
Bank Sta=   538.9,   553.9
Exp/Cntr=0.3,0.1

Type RM Length L Ch R = 1 ,14682.9,348.5,340.9,331.2
XS GIS Cut Line= 3
     1952680.314      426009.342     1952783.917      426127.072
     1953318.019      426382.558
#Sta/Elev= 30
       0 1347.18    19.6 1342.24    39.2 1338.02    68.6 1332.31    98.0 1326.96
   107.8 1325.42   127.4 1322.88   166.7 1318.80   184.8 1316.49   196.3 1315.25
   199.8 1315.29   206.2 1315.35   216.0 1316.58   235.8 1320.25   245.6 1322.51
   314.7 1341.06   433.1 1376.11   443.0 1378.84   452.9 1381.11   462.7 1382.31
   472.6 1382.66   502.2 1382.64   521.9 1383.04   561.4 1384.55   581.1 1385.52
   591.0 1386.24   600.9 1387.62   689.7 1403.91   719.3 1409.71   748.9 1416.01
#Mann= 3 , 0 , 0
       0     0.1       0   184.8   0.045       0   199.8     0.1       0
Bank Sta=   184.8,   199.8
Exp/Cntr=0.3,0.1

Type RM Length L Ch R = 1 ,14341.8,294,306.9,321.9
XS GIS Cut Line= 3
     1952193.349      426410.980     1952754.650      426463.891
     1953300.905      426467.593
#Sta/Elev= 30
       0 1394.94    29.7 1395.62    59.4 1395.47   168.2 1393.28   178.0 1392.94
   187.9 1392.12   197.8 1390.49   227.5 1382.87   296.7 1362.26   316.5 1356.99
   346.2 1351.37   395.6 1340.80   474.8 1324.98   534.1 1310.42   544.0 1308.54
   553.9 1307.86   556.3 1307.94   571.3 1308.93   613.4 1312.40   633.3 1315.13
   653.2 1318.55   832.0 1357.70   851.8 1361.65   891.6 1368.85   911.4 1372.88
   971.0 1386.94  1010.7 1395.45  1020.7 1397.26  1040.5 1399.68  1110.1 1403.83
#Mann= 3 , 0 , 0
       0     0.1       0   556.3   0.045       0   571.3     0.1       0
Bank Sta=   556.3,   571.3
Exp/Cntr=0.3,0.1

Type RM Length L Ch R = 1 ,14034.9,356.9,342.9,328.9
XS GIS Cut Line= 2
     1952562.584      426660.784     1953093.780      427089.495
#Sta/Elev= 30
       0 1340.34     9.9 1338.34    19.8 1336.11    29.7 1333.72    39.6 1331.08
    59.4 1325.35   118.7 1307.37   128.6 1305.59   130.6 1305.55   138.5 1305.39
   145.6 1306.37   148.4 1306.75   217.6 1321.14   267.1 1330.81   277.0 1333.05
   286.9 1335.84   336.4 1351.88   366.0 1361.05   435.3 1381.44   455.1 1387.15
   465.0 1389.80   474.9 1392.03   524.3 1399.68   544.1 1403.35   554.0 1405.53
   563.9 1408.36   573.8 1411.78   583.7 1415.72   662.8 1449.28   682.6 1457.13
#Mann= 3 , 0 , 0
       0     0.1       0   130.6   0.045       0   145.6     0.1       0
Bank Sta=   130.6,   145.6
Exp/Cntr=0.3,0.1

Type RM Length L Ch R = 1 ,13692,355.5,352,348.6
XS GIS Cut Line= 2
     1952225.090      427007.696     1952727.406      427040.661
#Sta/Elev= 30
       0 1357.43     9.9 1355.89    29.6 1352.43    39.5 1350.53    59.2 1346.34
    79.0 1341.77   118.4 1332.25   177.7 1318.79   217.2 1309.66   227.0 1307.19
   236.9 1304.45   247.3 1302.22   256.6 1301.38   262.3 1301.48   266.5 1301.56
   296.1 1303.85   325.7 1305.65   335.6 1305.98   355.3 1305.94   365.2 1306.06
   375.1 1306.62   385.0 1307.76   394.8 1309.52   404.7 1311.63   414.6 1313.93
   424.4 1316.45   434.3 1319.11   463.9 1327.39   493.5 1335.23   503.4 1338.25
#Mann= 3 , 0 , 0
       0     0.1       0   247.3   0.045       0   262.3     0.1       0
Bank Sta=   247.3,   262.3
Exp/Cntr=0.3,0.1

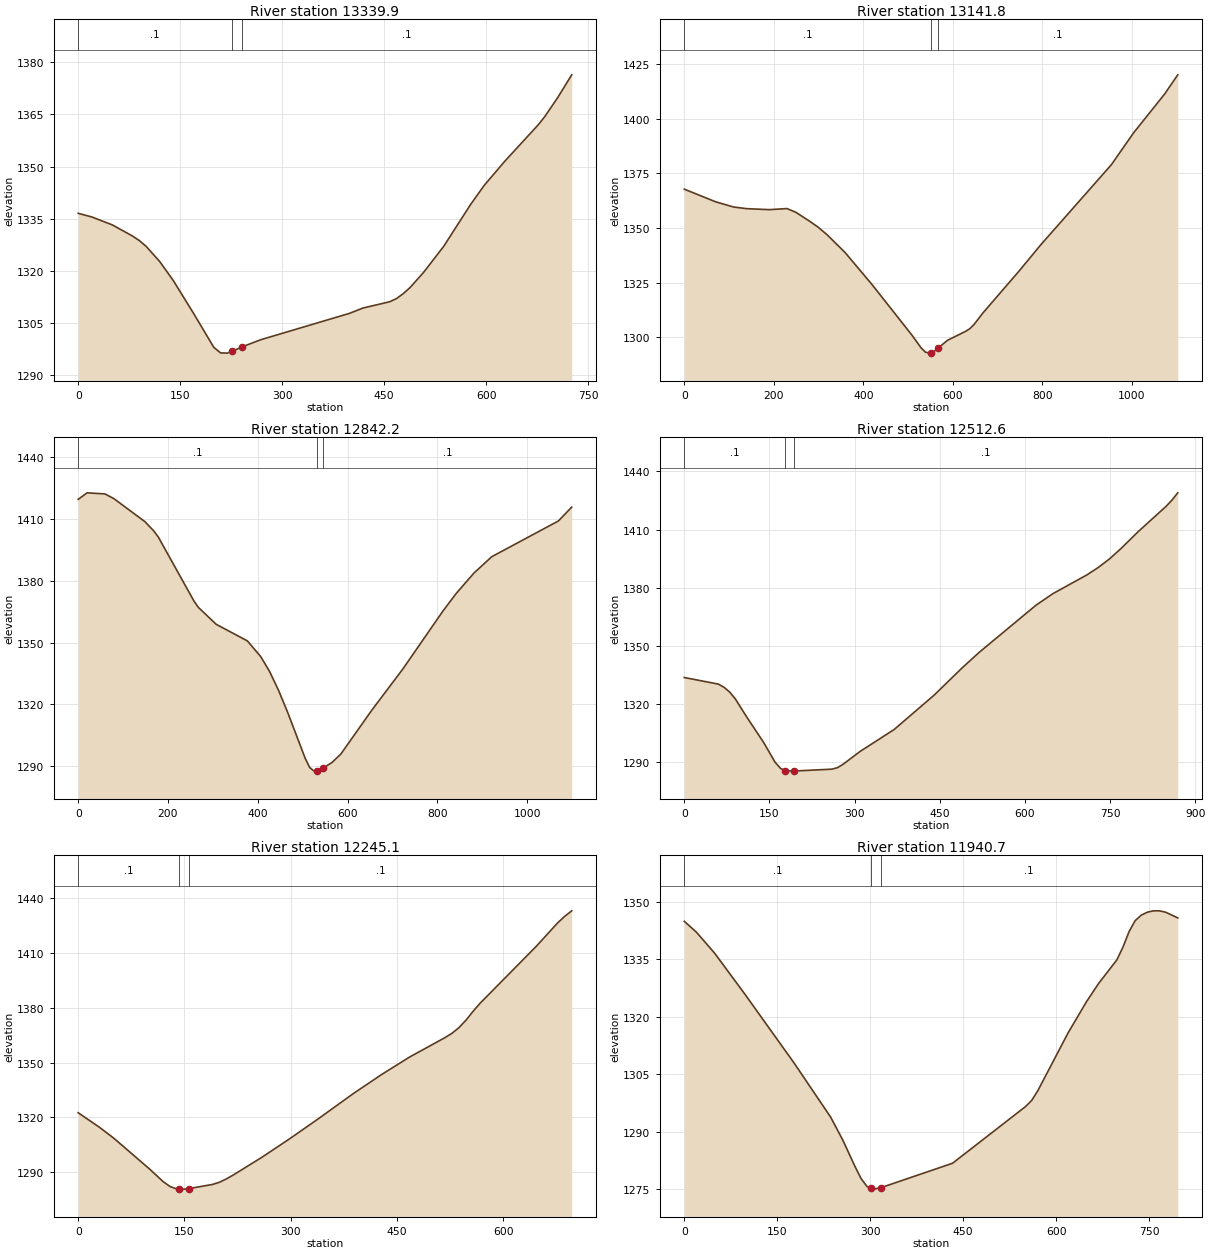
Type RM Length L Ch R = 1 ,13339.9,192.2,198.1,204.8
XS GIS Cut Line= 3
     1952272.182      427392.283     1952699.151      427354.609
     1952961.298      427214.902
#Sta/Elev= 30
       0 1336.58    19.9 1335.53    49.8 1333.28    79.7 1330.07    89.7 1328.77
    99.7 1327.13   119.6 1322.78   139.6 1317.33   169.5 1307.88   199.4 1298.08
   209.3 1296.48   219.3 1296.41     226 1296.91     241 1298.21   269.1 1300.30
   398.7 1307.82   418.7 1309.36   458.3 1311.18   468.2 1312.10   478.1 1313.51
   488.0 1315.25   507.8 1319.58   537.6 1327.12   577.2 1339.16   597.0 1344.59
   626.7 1351.40   676.2 1361.94   686.1 1364.35   705.9 1370.05   725.7 1376.36
#Mann= 3 , 0 , 0
       0     0.1       0     226   0.045       0     241     0.1       0
Bank Sta=     226,     241
Exp/Cntr=0.3,0.1

Type RM Length L Ch R = 1 ,13141.8,296.9,299.5,297.1
XS GIS Cut Line= 3
     1951956.601      427470.622     1952506.611      427568.554
     1953038.844      427679.951
#Sta/Elev= 30
       0 1367.81    69.8 1362.04   109.7 1359.65   139.7 1358.87   189.6 1358.42
   229.4 1358.92   249.4 1357.19   279.3 1353.22   299.3 1350.34   319.2 1346.89
   359.1 1338.80   419.0 1324.20   508.8 1300.86   528.7 1295.18   538.7 1293.13
   548.7 1292.68   551.2 1292.90   558.7 1293.56   566.2 1294.88   588.3 1298.59
   627.9 1302.60   637.8 1303.86   647.6 1305.90   667.4 1311.15   746.5 1329.95
   795.9 1342.21   954.1 1379.03  1003.6 1393.59  1072.8 1411.34  1102.4 1420.20
#Mann= 3 , 0 , 0
       0     0.1       0   551.2   0.045       0   566.2     0.1       0
Bank Sta=   551.2,   566.2
Exp/Cntr=0.3,0.1

Type RM Length L Ch R = 1 ,12842.2,343.2,329.4,320.7
XS GIS Cut Line= 3
     1951892.704      427695.635     1952415.028      427852.216
     1952969.146      427853.786
#Sta/Elev= 30
       0 1419.53    19.8 1422.69    59.5 1422.16    79.3 1419.90   148.7 1408.68
   168.5 1404.14   178.5 1401.20   257.8 1370.17   267.7 1367.06   307.4 1358.84
   376.8 1350.80   406.5 1343.19   426.3 1335.95   446.2 1326.83   466.0 1316.44
   505.6 1293.83   515.6 1289.34   525.5 1287.55     531 1287.69     546 1289.09
   565.1 1291.70   584.9 1295.79   654.1 1317.14   723.4 1337.19   812.4 1365.24
   842.1 1373.82   881.7 1383.75   921.3 1391.67  1069.7 1409.01  1099.4 1415.74
#Mann= 3 , 0 , 0
       0     0.1       0     531   0.045       0     546     0.1       0
Bank Sta=     531,     546
Exp/Cntr=0.3,0.1

Type RM Length L Ch R = 1 ,12512.6,274.7,267.5,259.7
XS GIS Cut Line= 3
     1952225.090      428244.651     1952350.669      428145.758
     1953008.742      427880.377
#Sta/Elev= 30
       0 1333.56    59.9 1330.16    69.9 1328.55    79.9 1326.05    89.9 1322.52
   109.9 1313.19   139.9 1299.96   159.8 1289.83   169.8 1286.56   178.1 1285.49
   189.8 1285.19   193.1 1285.24   259.8 1286.20   269.8 1286.98   279.8 1288.74
   309.8 1295.38   369.7 1306.69   439.7 1324.33   489.6 1338.56   519.6 1346.57
   619.6 1370.91   649.6 1376.92   709.5 1386.61   729.5 1390.44   749.5 1394.92
   769.5 1400.24   799.4 1408.85   849.4 1422.16   859.4 1425.31   869.4 1428.98
#Mann= 3 , 0 , 0
       0     0.1       0   178.1   0.045       0   193.1     0.1       0
Bank Sta=   178.1,   193.1
Exp/Cntr=0.3,0.1

Type RM Length L Ch R = 1 ,12245.1,288.2,304.4,320.7
XS GIS Cut Line= 3
     1952484.097      428379.649     1952557.875      428312.150
     1953036.684      427955.703
#Sta/Elev= 30
       0 1322.56    30.0 1314.59    50.0 1308.68   100.0 1291.97   119.9 1284.83
   129.8 1282.09   139.8 1280.70   141.8 1280.70   149.7 1280.69   156.8 1281.02
   189.5 1283.24   199.5 1284.46   209.4 1286.32   219.4 1288.53   259.2 1298.09
   299.0 1308.40   338.8 1319.17   388.5 1333.06   428.3 1343.47   468.1 1353.12
   517.8 1363.70   527.8 1366.09   537.7 1369.23   547.7 1373.32   557.6 1378.15
   567.6 1382.60   647.2 1413.92   677.0 1426.60   687.0 1430.20   696.9 1433.24
#Mann= 3 , 0 , 0
       0     0.1       0   141.8   0.045       0   156.8     0.1       0
Bank Sta=   141.8,   156.8
Exp/Cntr=0.3,0.1

Type RM Length L Ch R = 1 ,11940.7,292.2,298.9,304.5
XS GIS Cut Line= 3
     1952444.853      428481.682     1952846.707      428516.216
     1953239.516      428522.986
#Sta/Elev= 30
       0 1344.93    19.7 1342.07    49.2 1336.55    98.4 1325.75   177.1 1307.92
   236.1 1293.78   255.8 1287.75   275.4 1280.88   285.3 1277.69   295.1 1275.59
   301.9 1275.15   305.0 1274.95   316.9 1275.31   432.8 1281.71   550.7 1296.54
   560.5 1298.13   570.3 1300.64   619.4 1315.82   648.9 1323.92   668.5 1328.69
   698.0 1334.87   707.8 1338.20   717.6 1342.22   727.4 1345.09   737.3 1346.54
   747.1 1347.31   756.9 1347.67   766.7 1347.67   776.6 1347.31   796.2 1345.82
#Mann= 3 , 0 , 0
       0     0.1       0   301.9   0.045       0   316.9     0.1       0
Bank Sta=   301.9,   316.9
Exp/Cntr=0.3,0.1

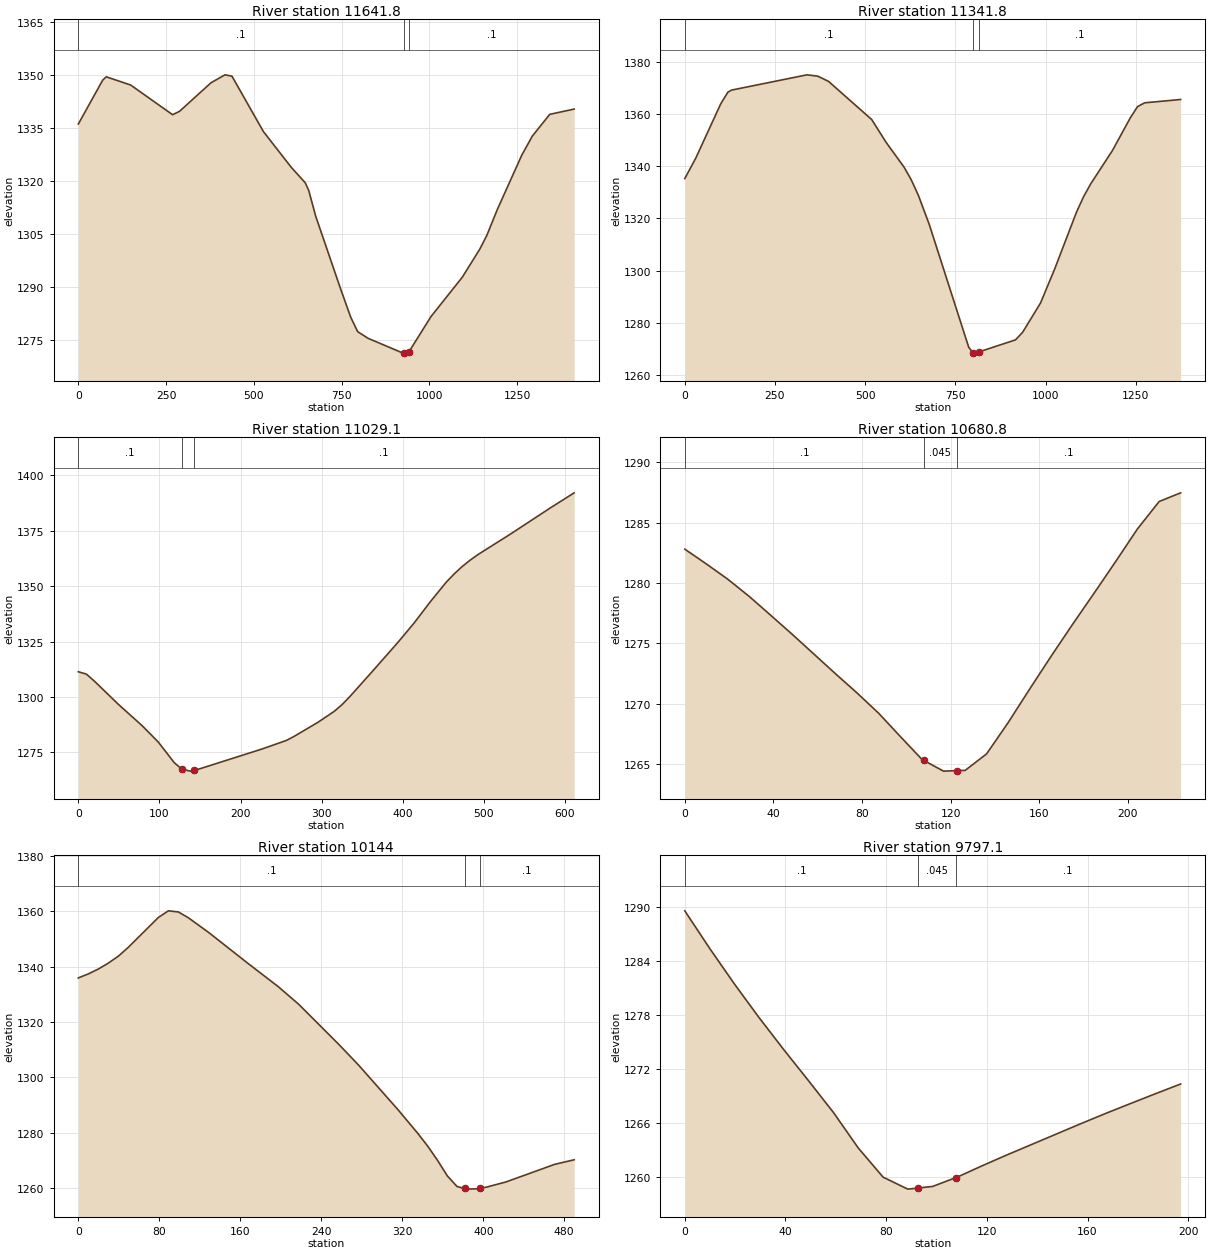
Type RM Length L Ch R = 1 ,11641.8,295.5,299.8,306.1
XS GIS Cut Line= 3
     1951869.709      428456.401     1952736.776      428805.279
     1953187.654      428962.247
#Sta/Elev= 30
       0 1336.07    69.6 1348.52    79.5 1349.44   149.1 1347.11   268.5 1338.70
   288.3 1339.67   377.8 1347.75   417.6 1350.00   437.5 1349.62   527.0 1333.94
   606.5 1323.79   646.3 1319.42   656.2 1317.22   676.1 1309.93   745.7 1289.72
   775.5 1281.40   795.4 1277.27   825.2 1275.37   924.7 1271.18   927.1 1271.18
   942.1 1271.64  1004.2 1281.52  1093.8 1292.73  1143.5 1300.67  1163.4 1304.54
  1193.2 1311.86  1262.8 1327.23  1292.7 1332.62  1342.4 1338.80  1412.0 1340.30
#Mann= 3 , 0 , 0
       0     0.1       0   927.1   0.045       0   942.1     0.1       0
Bank Sta=   927.1,   942.1
Exp/Cntr=0.3,0.1

Type RM Length L Ch R = 1 ,11341.8,313.9,312.6,310.5
XS GIS Cut Line= 3
     1951833.965      428507.026     1952505.233      428955.262
     1952964.699      429288.243
#Sta/Elev= 30
       0 1335.21    29.9 1342.86    99.6 1363.78   119.6 1368.28   129.6 1369.05
   338.8 1374.90   368.7 1374.39   398.6 1372.38   518.2 1357.78   558.0 1349.08
   607.9 1339.56   627.8 1334.73   647.7 1328.73   677.6 1317.69   787.2 1270.60
   799.7 1268.44   807.2 1268.38   814.7 1268.82   916.7 1273.45   936.6 1276.36
   986.4 1287.61  1026.2 1300.85  1085.9 1322.34  1105.8 1328.32  1125.7 1333.24
  1185.5 1345.91  1235.2 1358.46  1255.1 1362.73  1275.0 1364.19  1374.6 1365.46
#Mann= 3 , 0 , 0
       0     0.1       0   799.7   0.045       0   814.7     0.1       0
Bank Sta=   799.7,   814.7
Exp/Cntr=0.3,0.1

Type RM Length L Ch R = 1 ,11029.1,317.7,348.3,378.9
XS GIS Cut Line= 2
     1952325.553      429189.635     1952852.362      429499.675
#Sta/Elev= 30
       0 1311.44     9.9 1310.38    19.7 1307.24    49.3 1296.75    78.9 1287.02
    98.6 1279.70   118.3 1270.40   127.7 1267.44   138.0 1266.59   142.7 1266.99
   147.9 1267.43   226.8 1276.61   256.3 1280.41   266.2 1282.30   295.8 1288.71
   315.5 1293.56   325.4 1296.69   335.2 1300.41   364.8 1312.54   394.4 1324.85
   414.1 1333.49   433.8 1342.95   453.5 1351.81   463.4 1355.59   473.2 1358.91
   483.1 1361.81   493.0 1364.38   532.4 1373.48   581.7 1385.31   611.3 1392.18
#Mann= 3 , 0 , 0
       0     0.1       0   127.7   0.045       0   142.7     0.1       0
Bank Sta=   127.7,   142.7
Exp/Cntr=0.3,0.1

Type RM Length L Ch R = 1 ,10680.8,555.5,536.7,518.8
XS GIS Cut Line= 2
     1952204.683      429329.341     1952137.184      429542.826
#Sta/Elev= 26
       0 1282.80     9.7 1281.58    19.5 1280.30    29.2 1278.87    38.9 1277.31
    48.7 1275.72    58.4 1274.10    68.1 1272.48    77.9 1270.88    87.6 1269.21
    97.4 1267.28   107.1 1265.40   107.9 1265.32   116.8 1264.43   122.9 1264.47
   126.6 1264.49   136.3 1265.86   146.0 1268.44   155.8 1271.24   165.5 1273.96
   175.2 1276.60   185.0 1279.20   194.7 1281.81   204.4 1284.47   214.2 1286.74
   223.9 1287.46
#Mann= 3 , 0 , 0
       0     0.1       0   107.9   0.045       0   122.9     0.1       0
Bank Sta=   107.9,   122.9
Exp/Cntr=0.3,0.1

Type RM Length L Ch R = 1 ,10144,381.1,346.8,311.7
XS GIS Cut Line= 4
     1951666.452      428738.825     1951775.831      428993.184
     1951813.616      429061.406     1951879.545      429179.137
#Sta/Elev= 30
       0 1335.90     9.9 1337.36    19.8 1339.12    29.7 1341.27    39.6 1343.79
    49.4 1346.98    79.1 1357.77    89.0 1360.16    98.9 1359.75   108.8 1357.63
   128.6 1352.38   168.1 1341.01   197.8 1332.66   217.6 1326.40   257.1 1311.96
   276.9 1304.37   315.9 1288.22   335.4 1279.68   345.1 1275.11   354.9 1269.92
   364.5 1264.34   374.1 1260.50   381.5 1259.78   383.8 1259.55   393.4 1259.66
   396.5 1259.85   403.1 1260.26   422.3 1262.13   470.5 1268.50   489.8 1270.16
#Mann= 3 , 0 , 0
       0     0.1       0   381.5   0.045       0   396.5     0.1       0
Bank Sta=   381.5,   396.5
Exp/Cntr=0.3,0.1

Type RM Length L Ch R = 1 ,9797.1,257.6,255.4,250.7
XS GIS Cut Line= 2
     1951740.623      429469.931     1951918.396      429385.165
#Sta/Elev= 23
       0 1289.52     9.8 1285.38    19.7 1281.40    29.5 1277.66    39.4 1274.07
    49.2 1270.63    59.1 1267.10    68.9 1263.18    78.8 1259.93    88.6 1258.60
    92.6 1258.72    98.5 1258.90   107.6 1259.87   108.3 1259.94   118.2 1261.20
   128.0 1262.40   137.9 1263.57   147.7 1264.73   157.6 1265.90   167.4 1267.03
   177.2 1268.12   187.1 1269.21   197.0 1270.28
#Mann= 3 , 0 , 0
       0     0.1       0    92.6   0.045       0   107.6     0.1       0
Bank Sta=    92.6,   107.6
Exp/Cntr=0.3,0.1

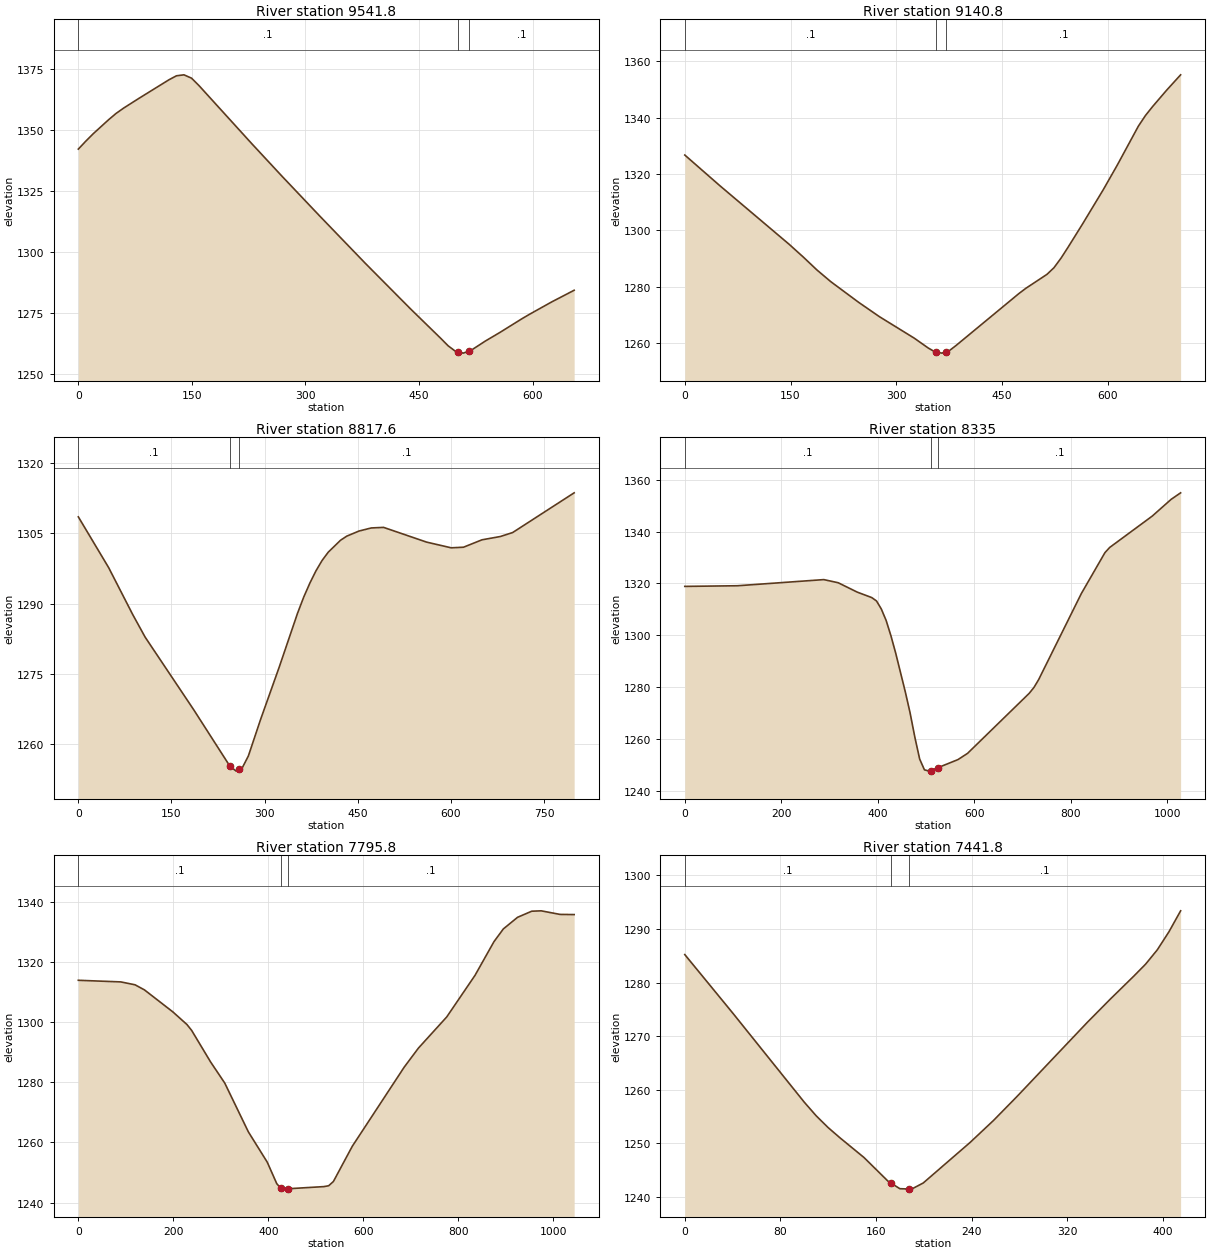
Type RM Length L Ch R = 1 ,9541.8,392,400.8,411.9
XS GIS Cut Line= 3
     1951549.460      429901.960     1951980.311      429632.279
     1952096.371      429542.826
#Sta/Elev= 30
       0 1342.17    10.0 1345.47    19.9 1348.54    39.9 1354.20    49.8 1356.80
    59.8 1358.99    79.7 1362.93   119.6 1370.60   129.6 1372.25   139.5 1372.65
   149.5 1371.28   159.5 1368.18   229.2 1344.35   269.1 1331.00   318.9 1314.68
   378.7 1295.40   438.5 1276.67   478.4 1264.58   488.4 1261.45   498.3 1259.14
   500.8 1258.97   508.3 1258.45   515.8 1259.24   518.1 1259.48   537.6 1263.42
   557.1 1267.00   586.4 1272.67   596.2 1274.45   625.5 1279.52   654.8 1284.25
#Mann= 3 , 0 , 0
       0     0.1       0   500.8   0.045       0   515.8     0.1       0
Bank Sta=   500.8,   515.8
Exp/Cntr=0.3,0.1

Type RM Length L Ch R = 1 ,9140.8,311,323.2,335.5
XS GIS Cut Line= 3
     1951944.417      429915.159     1952372.645      429844.216
     1952633.222      429775.148
#Sta/Elev= 30
       0 1326.69    49.3 1315.91   148.0 1295.04   167.7 1290.60   187.4 1285.94
   207.2 1281.76   246.6 1274.45   276.2 1269.34   325.6 1261.72   345.3 1258.25
   355.1 1256.83   356.2 1256.78   365.0 1256.41   371.2 1256.90   374.9 1257.19
   384.7 1259.07   474.0 1277.52   484.0 1279.41   513.9 1284.35   523.9 1286.72
   533.9 1290.11   543.9 1293.99   563.9 1302.01   593.8 1314.38   613.8 1323.16
   643.7 1336.96   653.7 1340.71   663.7 1343.85   683.7 1349.68   703.6 1355.15
#Mann= 3 , 0 , 0
       0     0.1       0   356.2   0.045       0   371.2     0.1       0
Bank Sta=   356.2,   371.2
Exp/Cntr=0.3,0.1

Type RM Length L Ch R = 1 ,8817.6,476.7,482.5,488.2
XS GIS Cut Line= 3
     1951931.548      430051.422     1952186.336      430151.785
     1952655.604      430386.420
#Sta/Elev= 30
       0 1308.53    48.9 1297.66    88.0 1287.54   107.6 1282.81   185.8 1267.29
   244.3 1255.18   254.3 1254.16   259.3 1254.53   264.1 1254.89   273.8 1257.39
   293.6 1265.24   323.3 1276.32   353.0 1287.91   362.9 1291.35   372.8 1294.34
   382.7 1296.99   392.6 1299.21   402.5 1300.98   422.3 1303.53   432.2 1304.40
   452.0 1305.50   471.8 1306.16   491.6 1306.28   560.9 1303.13   600.5 1301.91
   620.3 1302.04   650.0 1303.62   679.7 1304.33   699.5 1305.18   798.5 1313.67
#Mann= 3 , 0 , 0
       0     0.1       0   244.3   0.045       0   259.3     0.1       0
Bank Sta=   244.3,   259.3
Exp/Cntr=0.3,0.1

Type RM Length L Ch R = 1 ,8335,551.9,538.9,525.9
XS GIS Cut Line= 3
     1951495.161      430250.779     1951994.338      430611.819
     1952371.076      430778.211
#Sta/Elev= 30
       0 1318.87   109.3 1319.12   288.2 1321.49   318.0 1320.28   357.7 1316.64
   387.5 1314.56   397.5 1313.23   407.4 1310.14   417.3 1305.77   427.3 1299.84
   437.2 1293.11   457.1 1278.18   467.0 1270.08   477.0 1260.58   486.9 1252.20
   496.8 1248.04   506.8 1247.54   510.3 1247.75   525.3 1248.91   566.4 1252.00
   586.2 1254.40   714.1 1277.60   723.9 1279.87   733.7 1282.92   822.0 1316.08
   871.0 1331.90   880.8 1333.90   969.1 1346.02  1008.3 1352.49  1027.9 1355.00
#Mann= 3 , 0 , 0
       0     0.1       0   510.3   0.045       0   525.3     0.1       0
Bank Sta=   510.3,   525.3
Exp/Cntr=0.3,0.1

Type RM Length L Ch R = 1 ,7795.8,353.3,353.7,355.2
XS GIS Cut Line= 3
     1951204.759      430950.883     1951751.028      430979.138
     1952240.169      431066.729
#Sta/Elev= 30
       0 1313.87    89.5 1313.33   119.4 1312.37   139.2 1310.68   198.9 1303.38
   228.8 1299.15   238.7 1297.18   278.5 1286.72   308.3 1279.70   358.0 1263.48
   397.8 1253.40   417.7 1246.29     426 1244.75   427.6 1244.45     441 1244.57
   517.2 1245.29   527.1 1245.58   537.0 1246.98   576.8 1258.70   686.1 1285.00
   716.0 1291.32   775.6 1301.68   835.2 1315.52   875.0 1326.69   894.8 1330.94
   924.7 1334.80   954.5 1336.83   974.4 1336.96  1014.1 1335.77  1043.9 1335.71
#Mann= 3 , 0 , 0
       0     0.1       0     426   0.045       0     441     0.1       0
Bank Sta=     426,     441
Exp/Cntr=0.3,0.1

Type RM Length L Ch R = 1 ,7441.8,285.7,300.3,312.5
XS GIS Cut Line= 3
     1951561.090      431297.795     1951740.470      431309.720
     1951973.931      431335.469
#Sta/Elev= 23
       0 1285.21    40.0 1274.32    99.9 1257.66   109.9 1255.11   119.8 1252.93
   129.8 1251.00   149.8 1247.34   169.8 1242.94   172.3 1242.58   179.8 1241.51
   187.3 1241.45   189.6 1241.43   199.4 1242.58   238.5 1250.13   258.1 1254.24
   277.6 1258.68   336.4 1272.52   355.9 1276.92   375.5 1281.20   385.3 1283.42
   395.1 1286.10   404.9 1289.49   414.6 1293.38
#Mann= 3 , 0 , 0
       0     0.1       0   172.3   0.045       0   187.3     0.1       0
Bank Sta=   172.3,   187.3
Exp/Cntr=0.3,0.1

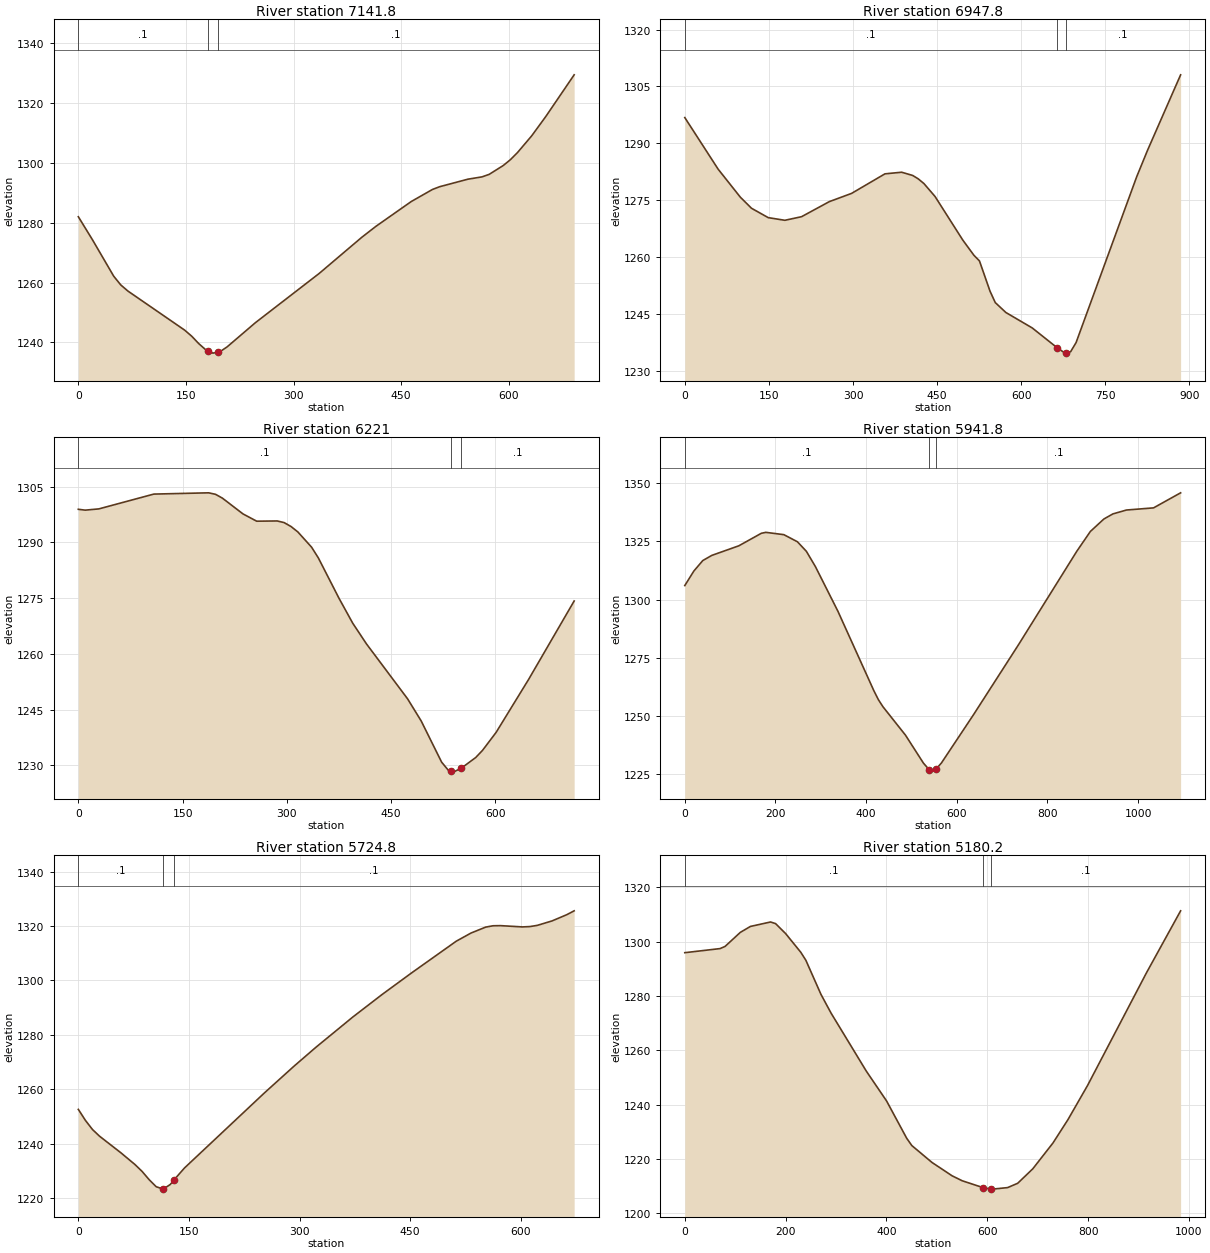
Type RM Length L Ch R = 1 ,7141.8,181.2,194,208.2
XS GIS Cut Line= 3
     1951502.967      431461.320     1951644.100      431584.899
     1952042.498      431892.646
#Sta/Elev= 30
       0 1282.03    19.8 1274.28    49.4 1262.10    59.2 1259.20    69.1 1257.16
   148.1 1244.10   158.0 1242.06   167.8 1239.58   177.7 1237.48   180.1 1237.22
   187.6 1236.39   195.1 1236.76   197.5 1236.88   207.3 1238.47   246.8 1246.58
   335.7 1263.06   394.9 1275.12   414.6 1278.79   464.0 1287.12   493.6 1291.16
   503.5 1292.07   542.9 1294.59   562.7 1295.37   572.6 1296.21   592.3 1299.18
   602.2 1301.13   612.0 1303.49   631.8 1309.09   651.5 1315.57   691.0 1329.51
#Mann= 3 , 0 , 0
       0     0.1       0   180.1   0.045       0   195.1     0.1       0
Bank Sta=   180.1,   195.1
Exp/Cntr=0.3,0.1

Type RM Length L Ch R = 1 ,6947.8,762.5,726.5,690.4
XS GIS Cut Line= 4
     1950937.701      431388.938     1951444.861      431526.927
     1951462.196      431629.010     1951534.404      431873.890
#Sta/Elev= 30
       0 1296.79    59.5 1283.19    99.2 1275.79   119.0 1272.89   148.8 1270.42
   178.5 1269.72   208.3 1270.67   257.8 1274.64   297.5 1276.81   357.0 1281.96
   386.8 1282.39   406.6 1281.53   416.5 1280.63   426.4 1279.42   446.3 1276.01
   495.8 1264.52   515.7 1260.50   525.6 1259.01   544.4 1251.05   553.8 1248.03
   572.7 1245.42   619.7 1241.35   664.4 1236.10   678.2 1234.71   679.4 1234.75
   688.1 1235.06   697.9 1237.48   805.9 1281.14   825.5 1288.21   884.4 1308.06
#Mann= 3 , 0 , 0
       0     0.1       0   664.4   0.045       0   679.4     0.1       0
Bank Sta=   664.4,   679.4
Exp/Cntr=0.3,0.1

Type RM Length L Ch R = 1 ,6221,270.7,279.3,289.5
XS GIS Cut Line= 4
     1950754.041      431712.697     1951167.275      431923.435
     1951298.943      431884.878     1951410.395      431899.005
#Sta/Elev= 30
       0 1298.91     9.9 1298.68    29.6 1299.02   108.6 1303.00   187.5 1303.34
   197.4 1302.94   207.3 1301.91   236.9 1297.67   256.6 1295.71   286.2 1295.77
   296.1 1295.33   306.0 1294.28   315.8 1292.83   335.6 1288.72   345.4 1285.81
   375.0 1274.99   394.8 1268.27   414.5 1262.72   473.7 1247.93   493.3 1241.97
   522.7 1230.89   532.5 1228.67     536 1228.60   542.3 1228.47     551 1229.26
   571.7 1232.12   581.5 1234.04   601.1 1238.89   647.9 1253.15   713.4 1274.24
#Mann= 3 , 0 , 0
       0     0.1       0     536   0.045       0     551     0.1       0
Bank Sta=     536,     551
Exp/Cntr=0.3,0.1

Type RM Length L Ch R = 1 ,5941.8,217.5,216.8,214.4
XS GIS Cut Line= 3
     1950663.507      432126.969     1951207.782      432175.016
     1951747.492      432266.386
#Sta/Elev= 30
       0 1305.98    19.9 1312.18    39.7 1316.70    59.6 1318.91   119.2 1323.02
   168.9 1328.39   178.8 1328.79   218.6 1327.79   248.4 1324.76   268.2 1320.66
   288.1 1314.12   337.8 1294.96   417.2 1260.85   427.2 1257.02   437.1 1254.04
   486.8 1241.86   526.5 1229.85   538.9 1227.10   546.4 1226.43   553.9 1227.19
   566.3 1229.98   636.0 1250.34   735.5 1280.41   864.9 1320.72   894.7 1329.17
   924.6 1334.52   944.5 1336.70   974.4 1338.36  1034.1 1339.28  1093.8 1345.73
#Mann= 3 , 0 , 0
       0     0.1       0   538.9   0.045       0   553.9     0.1       0
Bank Sta=   538.9,   553.9
Exp/Cntr=0.3,0.1

Type RM Length L Ch R = 1 ,5724.8,529.2,544.3,559.3
XS GIS Cut Line= 3
     1951077.610      432384.055     1951259.700      432395.043
     1951749.702      432405.435
#Sta/Elev= 30
       0 1252.67     9.6 1248.64    19.2 1245.28    28.8 1242.82    57.6 1236.76
    76.8 1232.43    86.4 1229.92    96.0 1226.88   105.6 1224.28   115.1 1223.39
   124.8 1225.12   130.1 1226.88   144.0 1231.16   252.4 1258.72   292.4 1268.50
   322.4 1275.51   372.5 1286.63   412.5 1294.96   452.5 1302.88   512.5 1314.41
   532.5 1317.41   552.5 1319.60   562.5 1320.09   572.5 1320.14   602.5 1319.67
   612.5 1319.80   622.5 1320.24   642.5 1321.87   662.5 1324.16   672.5 1325.58
#Mann= 3 , 0 , 0
       0     0.1       0   115.1   0.045       0   130.1     0.1       0
Bank Sta=   115.1,   130.1
Exp/Cntr=0.3,0.1

Type RM Length L Ch R = 1 ,5180.2,306.9,307.1,307.5
XS GIS Cut Line= 3
     1950637.696      432411.186     1951178.073      432931.894
     1951339.757      433099.856
#Sta/Elev= 30
       0 1295.89    70.0 1297.40    80.0 1298.21   110.1 1303.36   130.1 1305.55
   170.1 1307.19   180.1 1306.59   200.1 1302.91   230.1 1296.04   240.1 1293.13
   270.2 1280.52   290.2 1273.64   360.2 1252.26   400.2 1241.34   440.2 1227.59
   450.3 1224.91   490.3 1218.69   530.3 1213.76   550.3 1211.94   592.4 1209.37
   607.4 1208.88   610.4 1208.86   640.4 1209.42   660.4 1211.01   690.4 1216.35
   730.4 1225.85   760.1 1234.44   799.0 1247.02   915.6 1288.40   983.6 1311.30
#Mann= 3 , 0 , 0
       0     0.1       0   592.4   0.045       0   607.4     0.1       0
Bank Sta=   592.4,   607.4
Exp/Cntr=0.3,0.1

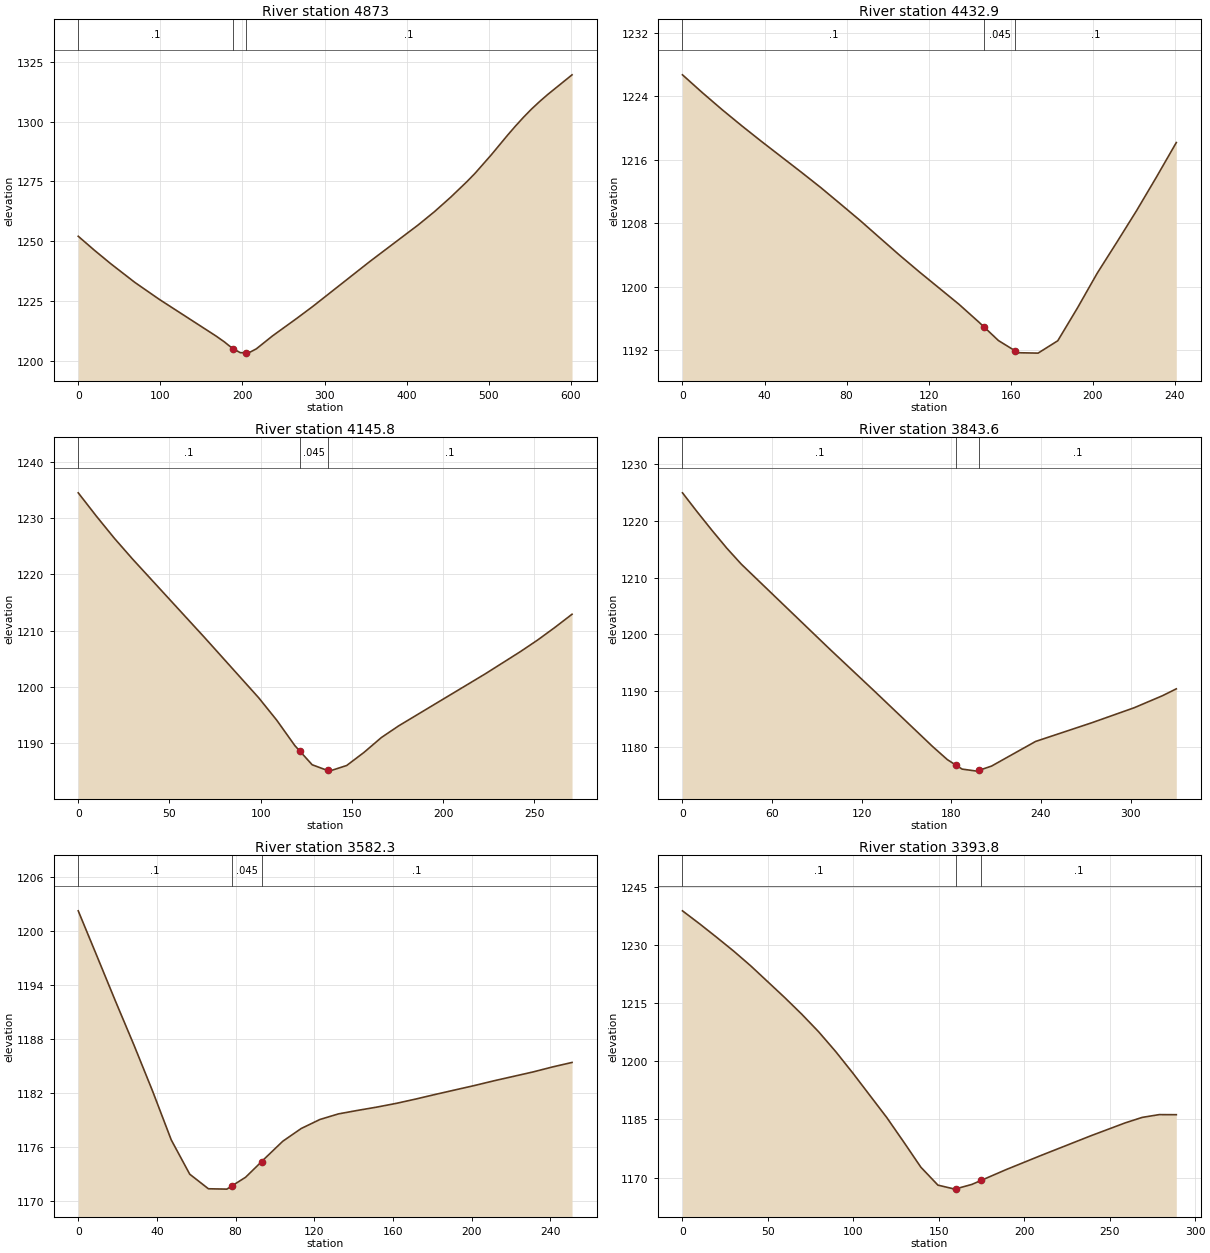
Type RM Length L Ch R = 1 ,4873,413.3,440.1,466.8
XS GIS Cut Line= 3
     1950724.419      432909.918     1950945.752      433106.135
     1951182.783      433299.213
#Sta/Elev= 30
       0 1252.06    19.7 1246.21    39.4 1240.63    69.0 1232.75    98.6 1225.70
   167.6 1210.39   177.5 1208.01   187.3 1205.32   189.1 1204.97   197.2 1203.40
   204.1 1203.25   207.0 1203.18   216.9 1204.96   236.6 1210.37   266.2 1217.71
   285.9 1222.76   355.0 1241.45   414.1 1256.80   433.8 1262.31   453.6 1268.37
   473.3 1274.85   483.2 1278.33   502.9 1286.02   522.6 1294.18   532.5 1298.11
   542.3 1301.80   552.2 1305.28   562.1 1308.44   571.9 1311.36   601.5 1319.58
#Mann= 3 , 0 , 0
       0     0.1       0   189.1   0.045       0   204.1     0.1       0
Bank Sta=   189.1,   204.1
Exp/Cntr=0.3,0.1

Type RM Length L Ch R = 1 ,4432.9,284.9,286.6,286.1
XS GIS Cut Line= 2
     1950581.572      433123.403     1950503.085      433351.015
#Sta/Elev= 28
       0 1226.73     9.6 1224.50    19.3 1222.34    28.9 1220.30    38.5 1218.33
    48.2 1216.39    57.8 1214.47    67.4 1212.51    77.0 1210.44    86.7 1208.33
    96.3 1206.14   105.9 1203.96   115.6 1201.84   125.2 1199.81   134.8 1197.78
   144.5 1195.53   147.1 1194.90   154.1 1193.19   162.1 1191.92   163.7 1191.66
   173.4 1191.61   183.0 1193.17   192.6 1197.31   202.2 1201.68   211.9 1205.64
   221.5 1209.62   231.1 1213.82   240.8 1218.18
#Mann= 3 , 0 , 0
       0     0.1       0   147.1   0.045       0   162.1     0.1       0
Bank Sta=   147.1,   162.1
Exp/Cntr=0.3,0.1

Type RM Length L Ch R = 1 ,4145.8,305.8,302.2,300.8
XS GIS Cut Line= 3
     1950379.076      432964.859     1950324.135      433070.031
     1950277.043      433214.447
#Sta/Elev= 21
       0 1234.50     9.9 1230.37    19.8 1226.42    29.7 1222.75    69.2 1208.78
    98.9 1198.05   108.8 1194.06   118.7 1189.55   121.6 1188.51   128.2 1186.14
   136.6 1185.13   137.6 1185.01   147.1 1186.01   156.6 1188.34   166.1 1190.98
   175.6 1193.06   223.1 1202.32   242.1 1206.22   251.6 1208.29   261.1 1210.54
   270.6 1212.91
#Mann= 3 , 0 , 0
       0     0.1       0   121.6   0.045       0   136.6     0.1       0
Bank Sta=   121.6,   136.6
Exp/Cntr=0.3,0.1

Type RM Length L Ch R = 1 ,3843.6,294.1,261.1,228
XS GIS Cut Line= 3
     1950080.825      432814.164     1950022.745      433043.346
     1950079.255      433118.693
#Sta/Elev= 19
       0 1224.99     9.8 1221.64    19.7 1218.37    29.6 1215.22    39.4 1212.37
    98.5 1197.37   128.1 1190.02   167.5 1180.11   177.3 1177.81   183.3 1176.79
   187.2 1176.13   197.0 1175.77   198.3 1175.89   206.9 1176.66   236.4 1181.02
   274.1 1184.33   302.4 1186.98   321.2 1189.09   330.6 1190.32
#Mann= 3 , 0 , 0
       0     0.1       0   183.3   0.045       0   198.3     0.1       0
Bank Sta=   183.3,   198.3
Exp/Cntr=0.3,0.1

Type RM Length L Ch R = 1 ,3582.3,213.5,188.5,163.5
XS GIS Cut Line= 3
     1949705.688      432970.206     1949837.473      433022.522
     1949940.781      433058.283
#Sta/Elev= 29
       0 1202.22     9.4 1197.25    18.9 1192.20    28.4 1187.27    37.8 1182.19
    47.3 1176.76    56.7 1172.95    66.2 1171.33    75.6 1171.29    78.3 1171.67
    85.1 1172.61    93.3 1174.36    94.5 1174.62   104.0 1176.61   113.4 1178.03
   122.9 1179.03   132.3 1179.65   141.8 1180.03   151.7 1180.40   161.7 1180.82
   171.6 1181.30   181.5 1181.81   191.5 1182.31   201.4 1182.80   211.4 1183.33
   221.3 1183.82   231.2 1184.31   241.2 1184.87   251.1 1185.37
#Mann= 3 , 0 , 0
       0     0.1       0    78.3   0.045       0    93.3     0.1       0
Bank Sta=    78.3,    93.3
Exp/Cntr=0.3,0.1

Type RM Length L Ch R = 1 ,3393.8,437.6,452,466.9
XS GIS Cut Line= 2
     1949741.761      433256.830     1949956.816      433063.752
#Sta/Elev= 25
       0 1238.77    10.0 1235.43    19.9 1231.98    29.9 1228.41    39.9 1224.60
    59.8 1216.42    69.8 1212.12    79.7 1207.58    89.7 1202.47    99.7 1196.94
   119.6 1185.45   129.6 1179.10   139.5 1172.68   149.5 1168.05   159.4 1167.02
   159.8 1167.07   169.4 1168.24   174.8 1169.27   189.4 1172.05   209.3 1175.61
   239.2 1180.81   259.1 1184.10   269.1 1185.52   279.0 1186.23   289.0 1186.21
#Mann= 3 , 0 , 0
       0     0.1       0   159.8   0.045       0   174.8     0.1       0
Bank Sta=   159.8,   174.8
Exp/Cntr=0.3,0.1