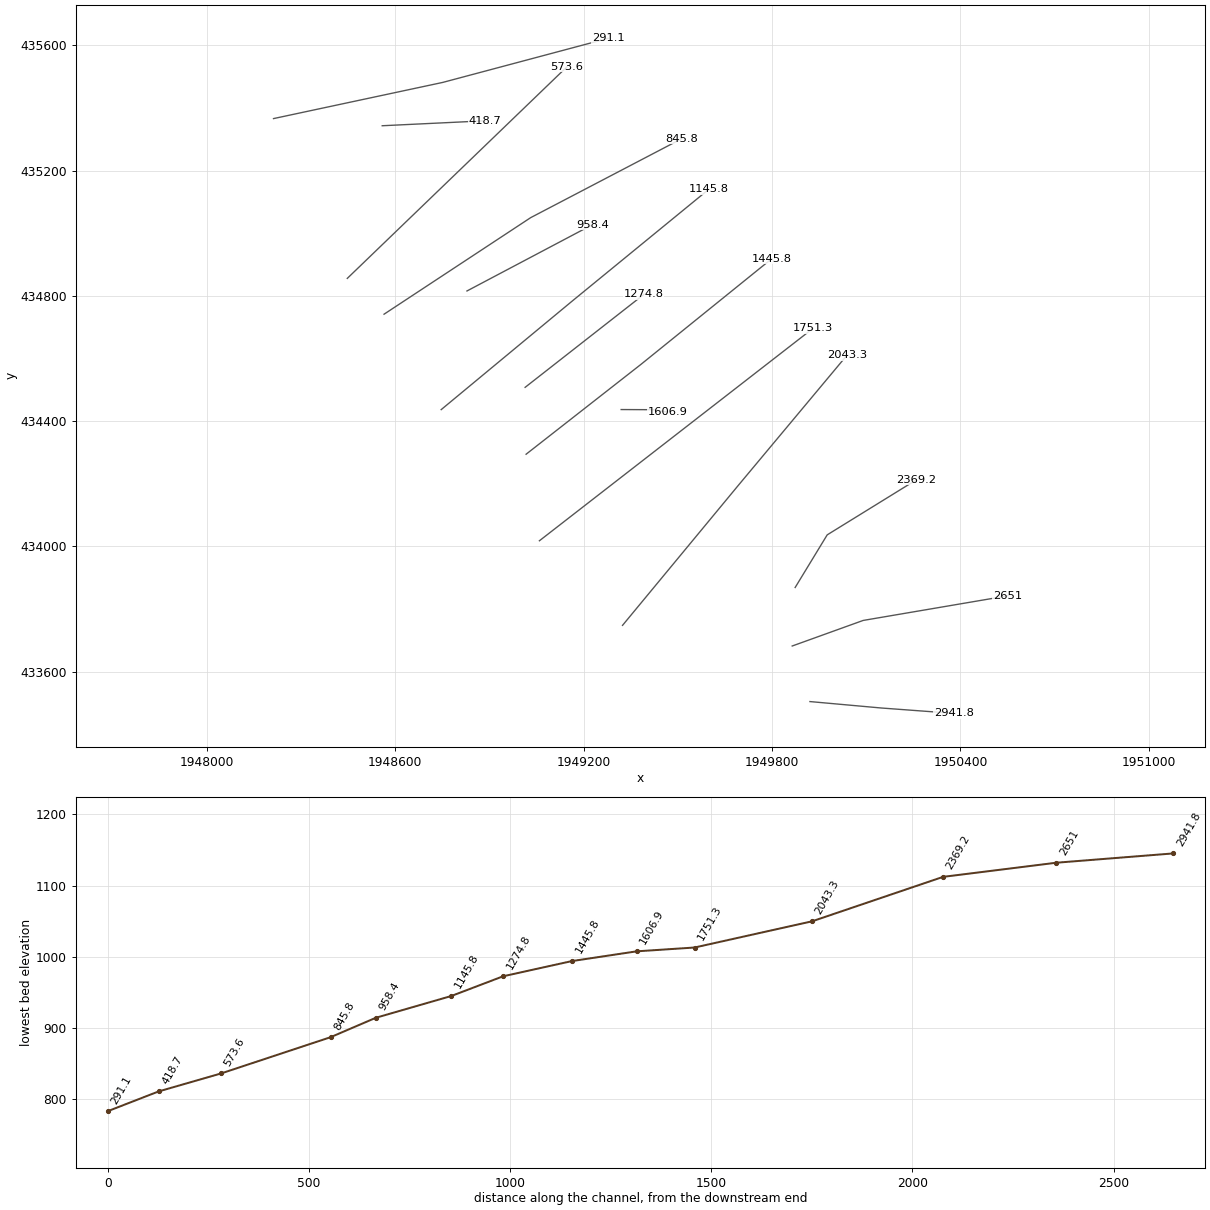
HEC-RAS study HrseshoeCk.prj: HrseshoeCk

--- HrseshoeCk.g01 (geometry) --- (continued)

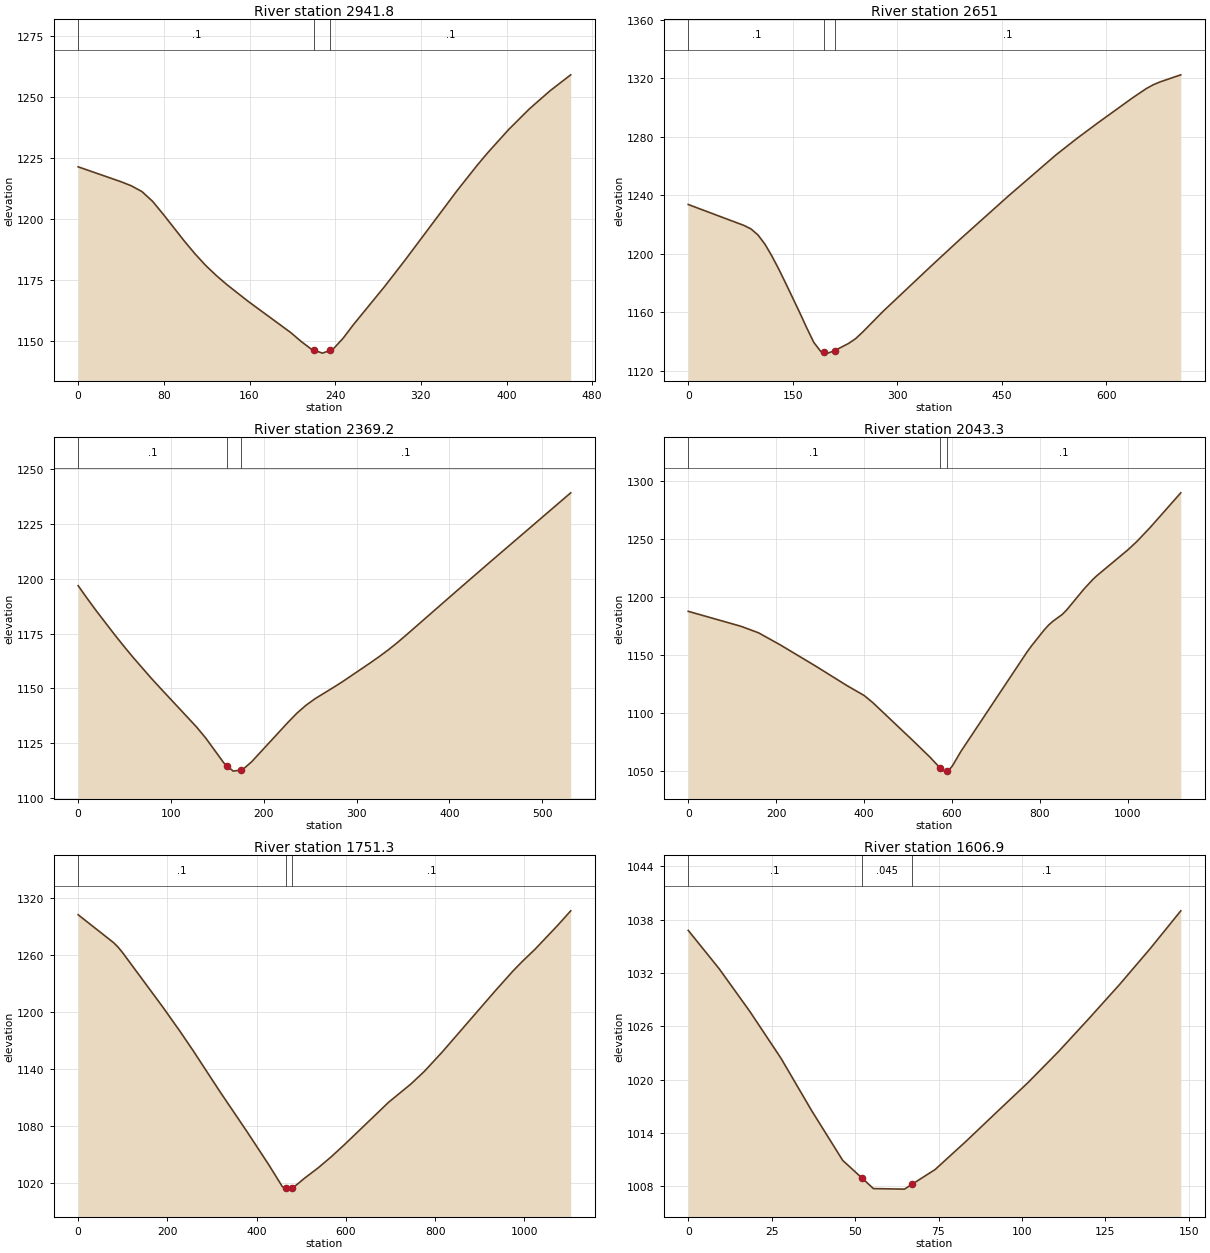
Type RM Length L Ch R = 1 ,2941.8,281,290.8,300.3
XS GIS Cut Line= 3
     1949920.712      433504.849     1950147.923      433484.338
     1950379.076      433467.176
#Sta/Elev= 30
       0 1221.46    39.7 1215.40    49.6 1213.69    59.5 1211.33    69.4 1207.36
    79.4 1202.03    99.2 1190.98   109.1 1185.78   119.0 1181.05   129.0 1176.88
   138.9 1173.14   158.7 1166.30   198.4 1153.52   208.3 1149.81   218.2 1146.52
   220.6 1146.17   228.1 1145.06   235.6 1146.24   237.8 1146.59   247.4 1151.18
   257.1 1156.78   286.1 1172.37   305.4 1183.30   353.7 1211.64   373.0 1222.33
   382.7 1227.38   402.0 1236.78   421.3 1245.22   440.6 1252.65   459.9 1259.19
#Mann= 3 , 0 , 0
       0     0.1       0   220.6   0.045       0   235.6     0.1       0
Bank Sta=   220.6,   235.6
Exp/Cntr=0.3,0.1

Type RM Length L Ch R = 1 ,2651,266.1,281.5,296.8
XS GIS Cut Line= 3
     1949864.201      433682.230     1950090.244      433763.856
     1950550.177      433842.343
#Sta/Elev= 30
       0 1233.72    80.1 1219.37    90.1 1216.98   100.1 1212.88   110.2 1206.47
   120.2 1198.35   130.2 1189.24   140.2 1179.49   160.2 1159.53   170.2 1149.16
   180.2 1139.35   190.3 1133.08   195.4 1132.53   200.3 1132.00   210.4 1133.74
   230.3 1138.69   240.3 1141.93   250.3 1146.41   280.0 1160.76   349.5 1192.00
   389.2 1209.51   458.7 1239.21   528.2 1267.83   558.0 1278.98   587.8 1289.55
   637.4 1306.60   657.3 1313.02   667.2 1315.61   677.1 1317.61   706.9 1322.46
#Mann= 3 , 0 , 0
       0     0.1       0   195.4   0.045       0   210.4     0.1       0
Bank Sta=   195.4,   210.4
Exp/Cntr=0.3,0.1

Type RM Length L Ch R = 1 ,2369.2,329.1,325.7,322.3
XS GIS Cut Line= 3
     1949873.620      433869.029     1949975.653      434036.991
     1950259.776      434212.802
#Sta/Elev= 30
       0 1196.86     9.8 1191.00    19.6 1185.34    39.3 1174.48    49.1 1169.29
    59.0 1164.21    78.6 1154.67    88.4 1150.14   127.7 1132.26   137.6 1127.19
   157.2 1115.77   160.4 1114.60   167.0 1112.18   175.4 1112.69   176.9 1112.78
   186.7 1116.37   226.0 1134.44   235.8 1138.70   245.7 1142.35   255.5 1145.33
   275.1 1150.42   285.0 1153.09   314.4 1161.53   324.3 1164.47   334.1 1167.56
   343.9 1170.88   353.8 1174.47   412.7 1196.28   442.2 1207.10   530.6 1239.26
#Mann= 3 , 0 , 0
       0     0.1       0   160.4   0.045       0   175.4     0.1       0
Bank Sta=   160.4,   175.4
Exp/Cntr=0.3,0.1

Type RM Length L Ch R = 1 ,2043.3,296.9,291.9,287
XS GIS Cut Line= 3
     1949323.709      433748.145     1949693.023      434195.610
     1950038.701      434610.425
#Sta/Elev= 30
       0 1187.60   120.0 1174.69   160.0 1169.06   210.1 1158.49   290.1 1140.32
   360.1 1123.77   400.1 1115.03   420.1 1108.76   510.2 1076.44   550.2 1061.72
   572.7 1052.58   580.2 1050.14   587.7 1049.90   590.2 1049.82   600.2 1053.97
   620.2 1066.86   770.2 1152.37   780.2 1157.58   810.2 1171.85   820.2 1176.00
   830.2 1179.27   850.2 1184.79   860.2 1188.55   900.2 1206.91   920.2 1215.10
   930.2 1218.60  1000.2 1240.71  1020.2 1247.76  1050.2 1259.75  1120.2 1289.77
#Mann= 3 , 0 , 0
       0     0.1       0   572.7   0.045       0   587.7     0.1       0
Bank Sta=   572.7,   587.7
Exp/Cntr=0.3,0.1

Type RM Length L Ch R = 1 ,1751.3,159.4,144.3,129.2
XS GIS Cut Line= 2
     1949058.925      434018.154     1949930.286      434696.079
#Sta/Elev= 30
       0 1302.59    79.6 1273.08    89.5 1268.45    99.5 1262.68   189.0 1205.67
   228.8 1179.26   258.6 1158.57   318.3 1115.60   378.0 1074.07   427.7 1038.46
   457.5 1015.86     465 1013.78   467.5 1013.09   477.4 1013.68     480 1014.48
   487.4 1016.77   507.2 1024.56   537.1 1035.22   566.9 1047.08   596.8 1060.01
   696.2 1104.90   746.0 1124.10   775.8 1137.28   815.6 1157.54   934.9 1222.34
   974.7 1243.30   994.6 1252.91  1024.4 1266.38  1074.2 1291.11  1104.0 1306.74
#Mann= 3 , 0 , 0
       0     0.1       0     465   0.045       0     480     0.1       0
Bank Sta=     465,     480
Exp/Cntr=0.3,0.1

Type RM Length L Ch R = 1 ,1606.9,145.4,160.7,176.3
XS GIS Cut Line= 3
     1949319.357      434437.054     1949421.176      434436.557
     1949466.373      434429.107
#Sta/Elev= 19
       0 1036.80     9.3 1032.47    18.5 1027.66    27.8 1022.41    37.0 1016.51
    46.3 1010.92      52 1008.96    55.5 1007.75    64.8 1007.69      67 1008.22
    74.0 1009.90    83.3 1013.09    92.6 1016.41   101.8 1019.67   111.0 1023.18
   120.1 1026.89   129.3 1030.73   138.5 1034.78   147.6 1039.00
#Mann= 3 , 0 , 0
       0     0.1       0      52   0.045       0      67     0.1       0
Bank Sta=      52,      67
Exp/Cntr=0.3,0.1

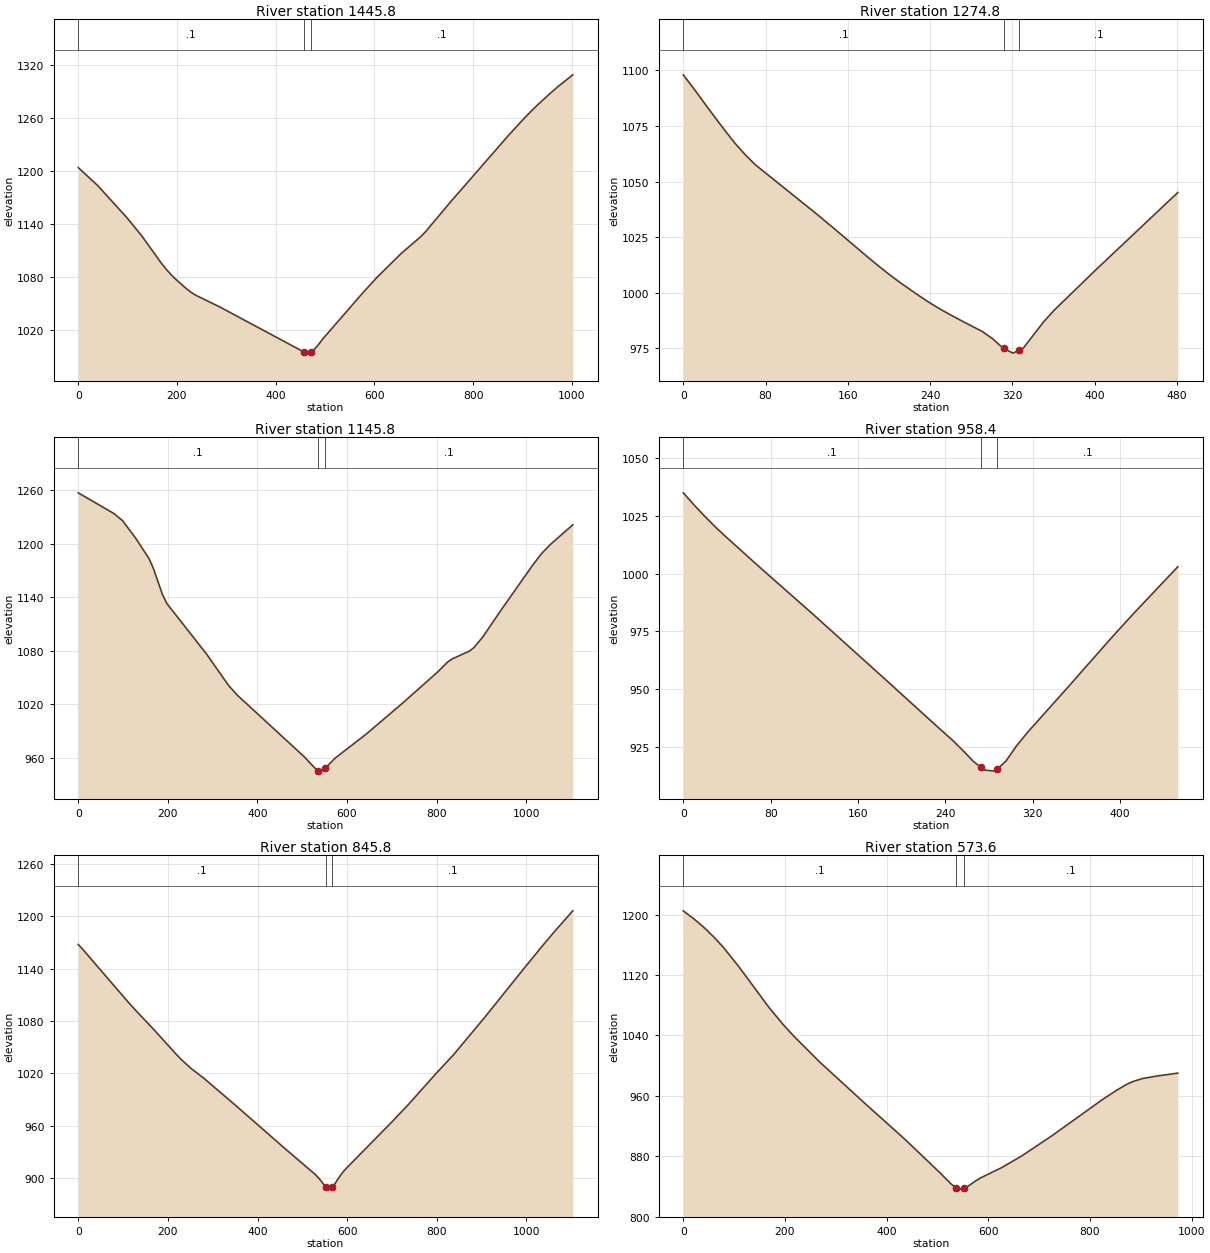
Type RM Length L Ch R = 1 ,1445.8,171,170.9,170.5
XS GIS Cut Line= 3
     1949016.542      434294.428     1949382.494      434581.337
     1949799.766      434919.131
#Sta/Elev= 30
       0 1203.65    39.6 1183.25    98.9 1146.85   128.6 1126.58   168.2 1095.70
   178.1 1088.89   188.0 1082.67   197.9 1077.32   217.7 1067.53   227.6 1063.12
   237.4 1059.62   286.9 1046.17   457.5  995.21   465.0  994.04   472.5  995.68
   475.0  996.23   484.9 1002.44   494.8 1009.66   574.4 1060.81   604.2 1079.07
   653.9 1106.41   693.7 1125.57   703.6 1131.21   753.3 1164.27   872.6 1240.63
   902.5 1258.77   922.3 1270.09   952.2 1285.59   972.0 1295.18  1001.9 1308.46
#Mann= 3 , 0 , 0
       0     0.1       0   457.5   0.045       0   472.5     0.1       0
Bank Sta=   457.5,   472.5
Exp/Cntr=0.3,0.1

Type RM Length L Ch R = 1 ,1274.8,128.1,128.8,129.3
XS GIS Cut Line= 2
     1949013.402      434507.913     1949391.709      434804.594
#Sta/Elev= 29
       0 1098.05    10.0 1091.96    30.0 1079.38    40.1 1073.22    50.1 1067.31
    60.1 1062.13    70.1 1057.53   130.2 1035.17   150.2 1027.43   180.3 1015.60
   190.3 1011.79   200.3 1008.13   210.3 1004.66   230.4  998.19   240.4  995.15
   250.4  992.37   260.4  989.79   270.4  987.32   290.5  982.52   300.5  979.31
   310.5  975.14   311.4  974.92   320.5  972.72   326.4  974.02   330.5  974.92
   350.6  986.97   360.6  992.05   400.6 1010.01   480.8 1045.06
#Mann= 3 , 0 , 0
       0     0.1       0   311.4   0.045       0   326.4     0.1       0
Bank Sta=   311.4,   326.4
Exp/Cntr=0.3,0.1

Type RM Length L Ch R = 1 ,1145.8,192,187.4,182.9
XS GIS Cut Line= 3
     1948746.094      434436.831     1949164.088      434783.898
     1949597.797      435139.549
#Sta/Elev= 30
       0 1257.28    79.0 1234.24    98.8 1226.14   128.4 1206.27   158.0 1183.51
   167.9 1172.27   187.7 1143.57   197.6 1133.24   286.5 1076.38   335.9 1040.99
   355.6 1030.04   503.8  961.53   533.4  945.80   535.8  945.62   543.3  945.04
   550.8  948.00   573.4  959.56   643.5  986.80   723.6 1021.11   803.7 1056.82
   823.7 1066.96   833.8 1070.66   873.8 1079.85   883.8 1083.81   903.9 1096.06
   943.9 1125.60  1014.0 1175.64  1034.1 1188.89  1054.1 1199.29  1104.2 1221.39
#Mann= 3 , 0 , 0
       0     0.1       0   535.8   0.045       0   550.8     0.1       0
Bank Sta=   535.8,   550.8
Exp/Cntr=0.3,0.1

Type RM Length L Ch R = 1 ,958.4,110.4,112.5,112.4
XS GIS Cut Line= 2
     1948828.173      434815.582     1949228.456      435027.497
#Sta/Elev= 24
       0 1035.00     9.8 1029.78    19.7 1024.83    29.5 1020.16    39.4 1015.82
    68.9 1003.25   118.2  982.70   187.1  953.36   226.5  936.42   246.2  928.07
   256.0  923.52   265.8  918.71   272.7  916.12   275.7  915.00   285.5  914.54
   287.7  915.50   295.4  918.84   305.2  925.49   315.1  931.22   354.5  952.05
   364.3  957.36   393.8  973.13   413.5  983.31   452.9 1003.00
#Mann= 3 , 0 , 0
       0     0.1       0   272.7   0.045       0   287.7     0.1       0
Bank Sta=   272.7,   287.7
Exp/Cntr=0.3,0.1

Type RM Length L Ch R = 1 ,845.8,268.1,272.2,278.4
XS GIS Cut Line= 3
     1948564.036      434741.405     1949031.223      435049.707
     1949512.739      435301.930
#Sta/Elev= 30
       0 1167.59    10.0 1162.02   110.0 1102.37   129.9 1091.08   169.9 1069.37
   219.9 1041.01   229.9 1035.76   249.9 1026.26   279.9 1014.43   349.8  983.76
   459.8  934.37   529.8  903.66   539.8  897.88   549.8  891.26   552.2  890.30
   559.7  887.29   567.2  890.16   569.6  891.08   579.5  898.95   589.4  906.18
   599.3  911.84   698.1  963.41   737.6  984.78   796.9 1019.00   836.5 1040.82
   905.7 1083.37   994.6 1140.22  1034.1 1165.06  1063.8 1183.13  1103.3 1206.11
#Mann= 3 , 0 , 0
       0     0.1       0   552.2   0.045       0   567.2     0.1       0
Bank Sta=   552.2,   567.2
Exp/Cntr=0.3,0.1

Type RM Length L Ch R = 1 ,573.6,171.2,154.9,138.8
XS GIS Cut Line= 2
     1948446.981      434855.768     1949146.830      435531.383
#Sta/Elev= 30
       0 1204.87    19.8 1194.81    39.7 1183.46    59.6 1170.56    79.4 1156.05
   109.2 1131.02   168.7 1076.86   198.5 1052.70   218.4 1038.35   268.0 1004.94
   357.3  949.91   436.8  901.88   506.2  857.30   526.1  843.74   536.7  838.08
   545.9  836.44   551.7  837.54   555.9  838.34   575.7  847.60   585.6  851.61
   625.3  864.58   665.0  880.05   724.6  906.85   823.9  954.70   853.6  967.85
   873.5  975.59   883.4  978.61   903.3  982.85   933.0  986.32   972.8  990.03
#Mann= 3 , 0 , 0
       0     0.1       0   536.7   0.045       0   551.7     0.1       0
Bank Sta=   536.7,   551.7
Exp/Cntr=0.3,0.1

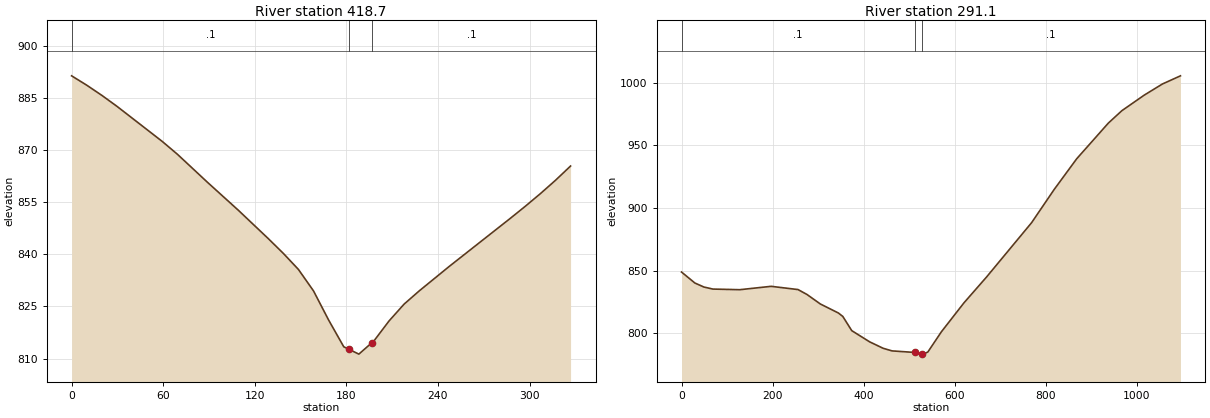
Type RM Length L Ch R = 1 ,418.7,123.2,126.9,130.6
XS GIS Cut Line= 2
     1948558.178      435343.015     1948884.683      435358.712
#Sta/Elev= 27
       0  891.35     9.9  888.66    19.8  885.73    29.7  882.58    59.4  872.47
    69.3  868.79    89.2  860.64   109.0  852.77   128.8  844.54   138.7  840.27
   148.6  835.65   158.5  829.46   168.4  821.08   178.3  813.40   181.8  812.65
   188.2  811.28   196.8  814.59   198.1  815.09   208.0  820.84   217.9  825.69
   227.8  829.49   247.6  836.58   287.3  850.30   297.2  853.80   307.1  857.44
   317.0  861.28   326.9  865.40
#Mann= 3 , 0 , 0
       0     0.1       0   181.8   0.045       0   196.8     0.1       0
Bank Sta=   181.8,   196.8
Exp/Cntr=0.3,0.1

Type RM Length L Ch R = 1 ,291.1,288.5,291.1,293.8
XS GIS Cut Line= 3
     1948211.998      435365.854     1948751.049      435481.336
     1949277.841      435622.041
#Sta/Elev= 30
       0  848.96    29.5  840.18    49.2  837.01    68.9  835.37   128.0  834.87
   196.9  837.56   256.0  834.98   275.6  831.09   305.2  823.45   344.6  816.31
   354.4  813.56   374.1  802.21   413.5  793.25   443.0  788.14   462.7  786.04
   512.6  784.80   527.6  783.71   531.6  783.46   541.4  785.17   571.1  801.29
   620.7  824.38   670.2  844.93   769.4  888.37   819.0  914.86   868.5  939.36
   937.9  967.76   967.7  977.71  1017.2  990.20  1056.9  999.02  1096.5 1005.53
#Mann= 3 , 0 , 0
       0     0.1       0   512.6   0.045       0   527.6     0.1       0
Bank Sta=   512.6,   527.6
Exp/Cntr=0.3,0.1